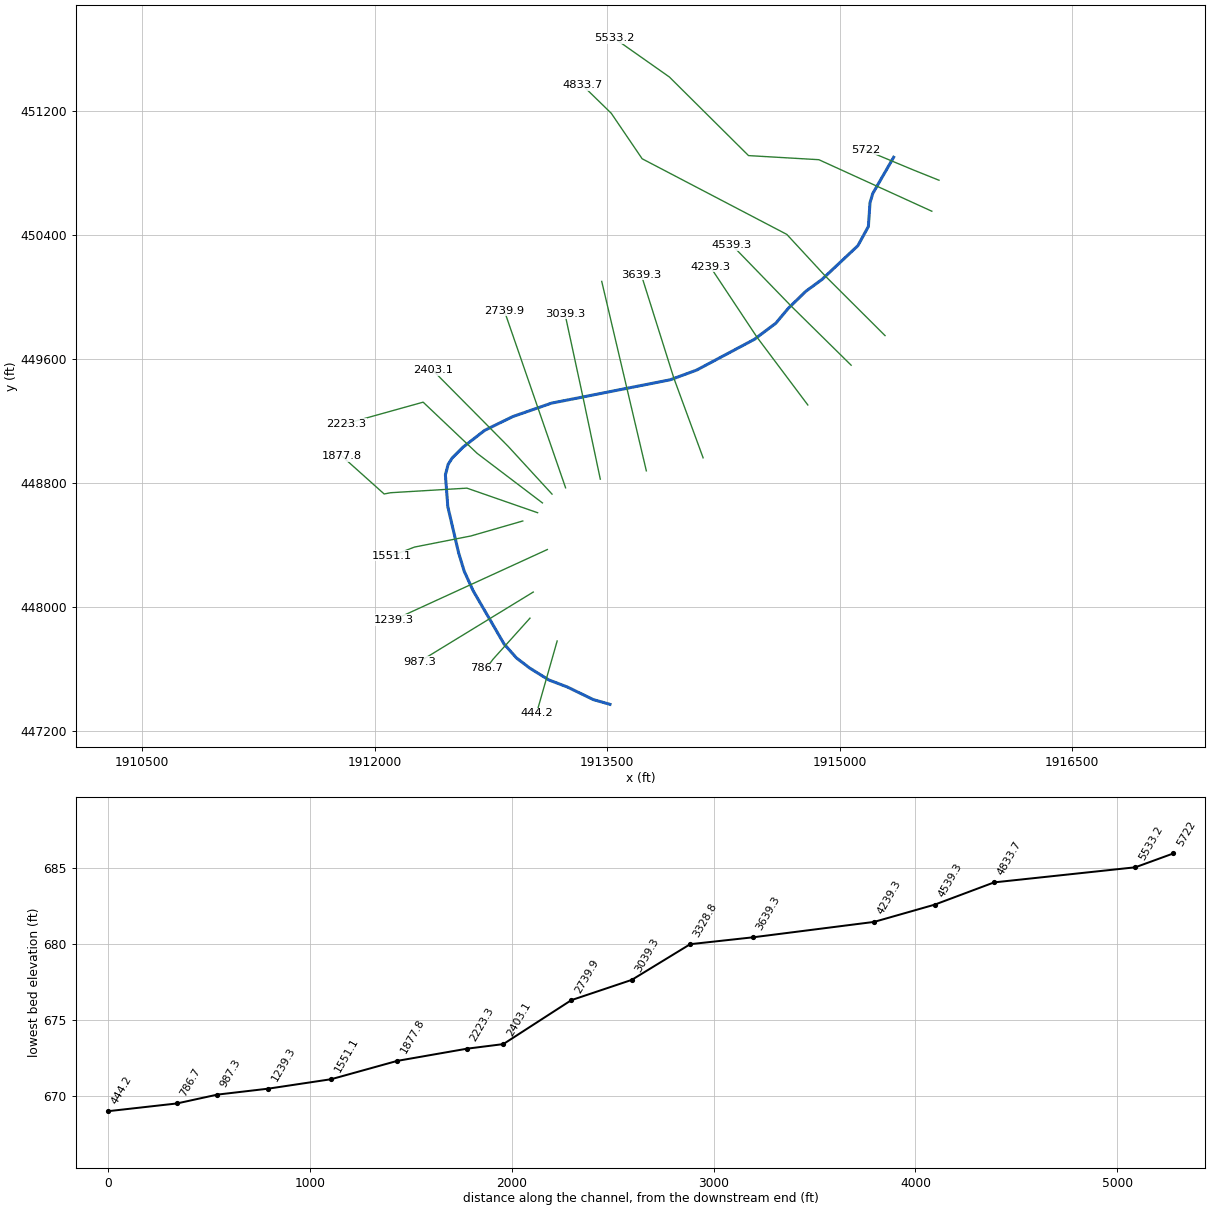
--- TwentyMiCk.prj (project) ---

Proj Title=TwentyMiCk
Current Plan=p01
Default Exp/Contr=0,0
English Units
Geom File=g01
Flow File=f01
Plan File=p01
BEGIN DESCRIPTION:
END DESCRIPTION:
DSS Export Rating Curves= 0
DSS Export Rating Curve Sorted= 0
DSS Export Volume Flow Curves= 0
DXF OffsetX= 0
DXF OffsetY= 0
DXF ScaleX= 0
DXF ScaleY= 0

--- TwentyMiCk.p01 (plan) ---

Plan Title=Floodplain
Program Version=4.00
Geom File=g01
Flow File=f01
K Sum by GR=0
Std Step Tol=0.01
Critical Tol=0.01
Num of Std Step Trials=20
Max Error Tol=0.3
Flow Tol Ratio=0.001
Split Flow NTrial=30
Split Flow Tol=0.02
Split Flow Ratio=0.02
Log Output Level=0
Friction Slope Method=1
Unsteady Friction Slope Method=2
Unsteady Bridges Friction Slope Method=1
Global Log Level=0
CheckData=False
Run HTab=0
Run UNet=0
Run PostProcess=0
UNET Theta=0
UNET Theta Warmup=0
UNET ZTol=0
UNET ZSATol=0
UNET MxIter=0
UNET MaxInSteps=0
UNET DtIC=0
UNET DtMin=0
UNET MaxCRTS=0
UNET WFStab=0
UNET SFStab=0
UNET WFX=0
UNET SFX=0
UNET DSS MLevel=0
UNET DZMax Abort=0
UNET Convert EG Bridges=0
UNET Use Existing IB Tables=0
UNET Froude Limit=0
UNET Froude Power=0
Write IC File=0
Echo Input=False
Echo Output=False
Write Detailed=0

--- TwentyMiCk.f01 (steady flow) ---

Flow Title=NFF Regression Equation
Program Version=4.00
Number of Profiles=1
Profile Names=P100yr
River Rch & RM=TwentyMiCk,Main      ,5722
7082.993
River Rch & RM=TwentyMiCk,Main      ,4833.7
10389.32
Boundary for River Rch & Prof#=TwentyMiCk,Main      ,1
Up Type=0
Dn Type=3
Dn Slope=0.003492

--- TwentyMiCk.g01 (geometry) ---

Geom Title=USGS 3m DEM
Program Version=4.10

River Reach=TwentyMiCk      ,Main
Reach XY= 30
     1915349.033      450902.106     1915214.342      450668.501
     1915196.453      450608.522     1915185.888      450454.979
      1915117.64      450330.846     1914886.727      450113.644
     1914782.561      450037.255     1914669.714       449927.88
     1914588.116      449830.658     1914449.227      449726.491
       1914077.7      449528.574     1913907.561      449466.074
       1913140.2      449315.033     1912890.199      449228.227
     1912709.644      449139.685     1912569.019      449030.311
     1912500.449       448961.74     1912473.492      448919.439
     1912456.172      448851.491     1912471.797       448646.63
     1912541.241      448349.755     1912577.699      448229.963
     1912634.991      448104.963     1912834.644      447761.213
     1912914.505      447670.935     1912999.611      447605.907
     1913123.198      447529.164      1913242.63      447483.435
     1913411.033      447401.838      1913518.36      447371.404

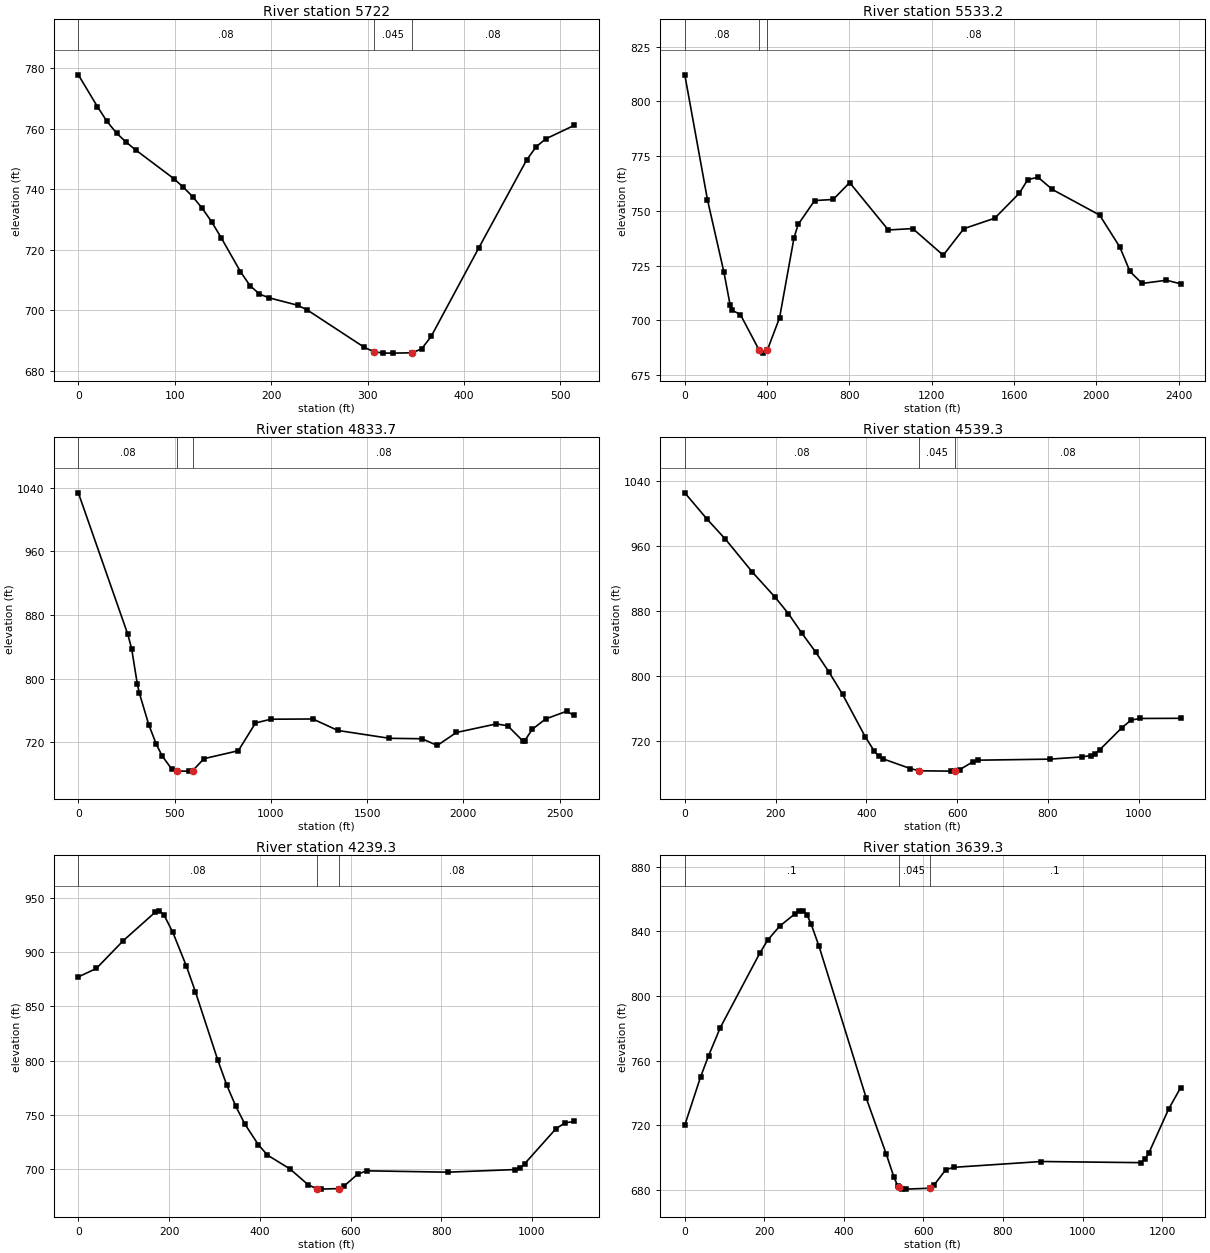
Type RM Length L Ch R = 1 ,5722    ,189.4,188.7,187.9
XS GIS Cut Line= 3
     1915641.565      450753.736     1915476.358      450820.029
     1915165.937      450949.459
#Sta/Elev= 30
       0  777.74    19.8  767.25    29.7  762.39    39.6  758.53    49.4  755.59
    59.3     753    98.9  743.53   108.8   740.7   118.7  737.52   128.6  733.68
   138.4   729.2   148.3  723.93   168.1  712.85     178  708.23   187.9  705.41
   197.8  704.18   227.5  701.73   237.4  700.18   296.7  687.83   306.6  686.38
   316.5  685.95   326.4  685.93   346.2  686.04   356.1  687.34     366  691.45
   415.4  720.66   464.9  749.59   474.8  753.98   484.7  756.59   514.3  761.05
#Mann= 3 , 0 , 0
       0     .08       0   306.6    .045       0   346.2     .08       0
Bank Sta=306.6,346.2
XS Rating Curve= 0 ,0
Exp/Cntr=0.3,0.1

Type RM Length L Ch R = 1 ,5533.2  ,707.6,699.5,690.6
XS GIS Cut Line= 5
     1915595.265      450553.804     1914866.486      450886.277
     1914412.488      450912.745     1913901.377      451420.274
     1913547.033      451669.526
#Sta/Elev= 30
       0  812.18   110.1  755.11   190.2  721.97   220.3  707.01   230.3  704.63
   270.4   702.6   360.5  686.53   380.5  685.02   400.5  686.26   460.6  701.22
   530.7  737.71   550.7   743.8   630.8  754.73   720.9  755.22     801  762.93
   988.9  741.29  1107.5  741.93  1255.8  729.75  1355.8  741.88  1505.9  746.66
    1626  758.12    1666  764.26    1716  765.41    1786  759.79  2015.5  748.12
  2113.9  733.49  2163.2  722.32  2222.2  716.86  2340.4  718.32  2409.3   716.7
#Mann= 3 , 0 , 0
       0     .08       0   360.5    .045       0   400.5     .08       0
Bank Sta=360.5,400.5
XS Rating Curve= 0 ,0
Exp/Cntr=0.3,0.1

Type RM Length L Ch R = 1 ,4833.7  ,294.3,294.5,295
XS GIS Cut Line= 6
      1915293.38      449751.089     1914908.392      450134.933
     1914659.497       450404.27     1913725.763      450892.382
     1913526.466      451186.021     1913342.502      451365.224
#Sta/Elev= 30
       0 1033.39     257   855.7   276.8   837.9   306.4   793.4   316.3  782.53
   365.7  742.41   405.3  717.68   434.9  703.33   484.3  686.84     514  684.08
   573.4  684.03   593.2  684.39   652.7  699.68   831.1  709.63   920.3  744.45
   999.8   749.2  1218.5  749.49  1347.7  735.09  1616.1  725.23  1785.1  724.67
  1864.6  716.24    1964  732.53    2171  743.28  2230.2  741.02    2309  721.95
  2318.9   722.2  2358.4   736.6  2427.5  749.53  2536.2  759.15  2575.7  753.92
#Mann= 3 , 0 , 0
       0     .08       0     514    .045       0   593.2     .08       0
Bank Sta=514,593.2
XS Rating Curve= 0 ,0
Exp/Cntr=0.3,0.1

Type RM Length L Ch R = 1 ,4539.3  ,303.4,300,295.8
XS GIS Cut Line= 3
     1915074.693      449559.982     1914685.682      449943.357
     1914305.702        450335.4
#Sta/Elev= 30
       0 1025.29    49.6  992.51    89.4  968.29     149  927.54   198.6  896.92
   228.4  876.37   258.2  852.15     288  829.42   317.8   804.4   347.6  777.02
   397.2  725.12   417.1  707.37     427     701   436.9  697.63   496.5  685.78
   516.4  682.95   585.9  682.57   595.8  682.85   605.7  684.48   635.5  694.33
   645.4  696.04   804.3  697.34   873.8  700.02   893.6  701.72   903.5  704.17
   913.5  708.63   963.1  736.24     983  745.41  1002.8  747.42  1092.1  747.62
#Mann= 3 , 0 , 0
       0     .08       0   516.4    .045       0   595.8     .08       0
Bank Sta=516.4,595.8
XS Rating Curve= 0 ,0
Exp/Cntr=0.3,0.1

Type RM Length L Ch R = 1 ,4239.3  ,606.6,600,593.7
XS GIS Cut Line= 3
     1914794.931      449303.513     1914467.448      449740.156
        1914165.      450196.065
#Sta/Elev= 30
       0  877.19    39.7  884.97    99.2  910.68   168.7   936.6   178.6  938.14
   188.6  934.55   208.4  918.15   238.2  887.14     258  863.54   307.6  800.18
   327.5  777.07   347.3  757.66   367.2  741.34     397   722.3   416.8  712.86
   466.4   700.1   506.1  685.64     526  681.65   535.9  681.44   575.6  681.98
   585.6  684.21   615.4  695.15   635.3  698.34   814.4  697.08   963.6   699.5
   973.5  700.99   983.5  704.72  1053.1  737.33    1073  742.59  1092.9  743.84
#Mann= 3 , 0 , 0
       0     .08       0     526    .045       0   575.6     .08       0
Bank Sta=526,575.6
XS Rating Curve= 0 ,0
Exp/Cntr=0.3,0.1

Type RM Length L Ch R = 1 ,3639.3  ,313.2,310.5,308.8
XS GIS Cut Line= 3
      1914119.35      448962.343     1913931.125      449474.731
     1913720.374      450143.001
#Sta/Elev= 30
       0   720.1    39.7  749.93    59.6  762.94    89.3  780.46   188.6  826.58
   208.4  834.64   238.2  843.18   277.9   851.1   287.8   852.6   297.8  852.76
   307.7     850   317.6  844.57   337.4  830.86   456.5  736.57   506.2  702.36
     526  687.71   535.9   682.2   538.4  681.79   545.9  680.56   555.9  680.43
   615.9  680.99     626  682.74     656  692.41     676  693.93   896.2  697.53
  1146.5  696.82  1156.5  698.86  1166.5   702.7  1216.6  730.08  1246.6  743.24
#Mann= 3 , 0 , 0
       0      .1       0   538.4    .045       0   615.9      .1       0
Bank Sta=538.4,615.9
XS Rating Curve= 0 ,0
Exp/Cntr=0.3,0.1

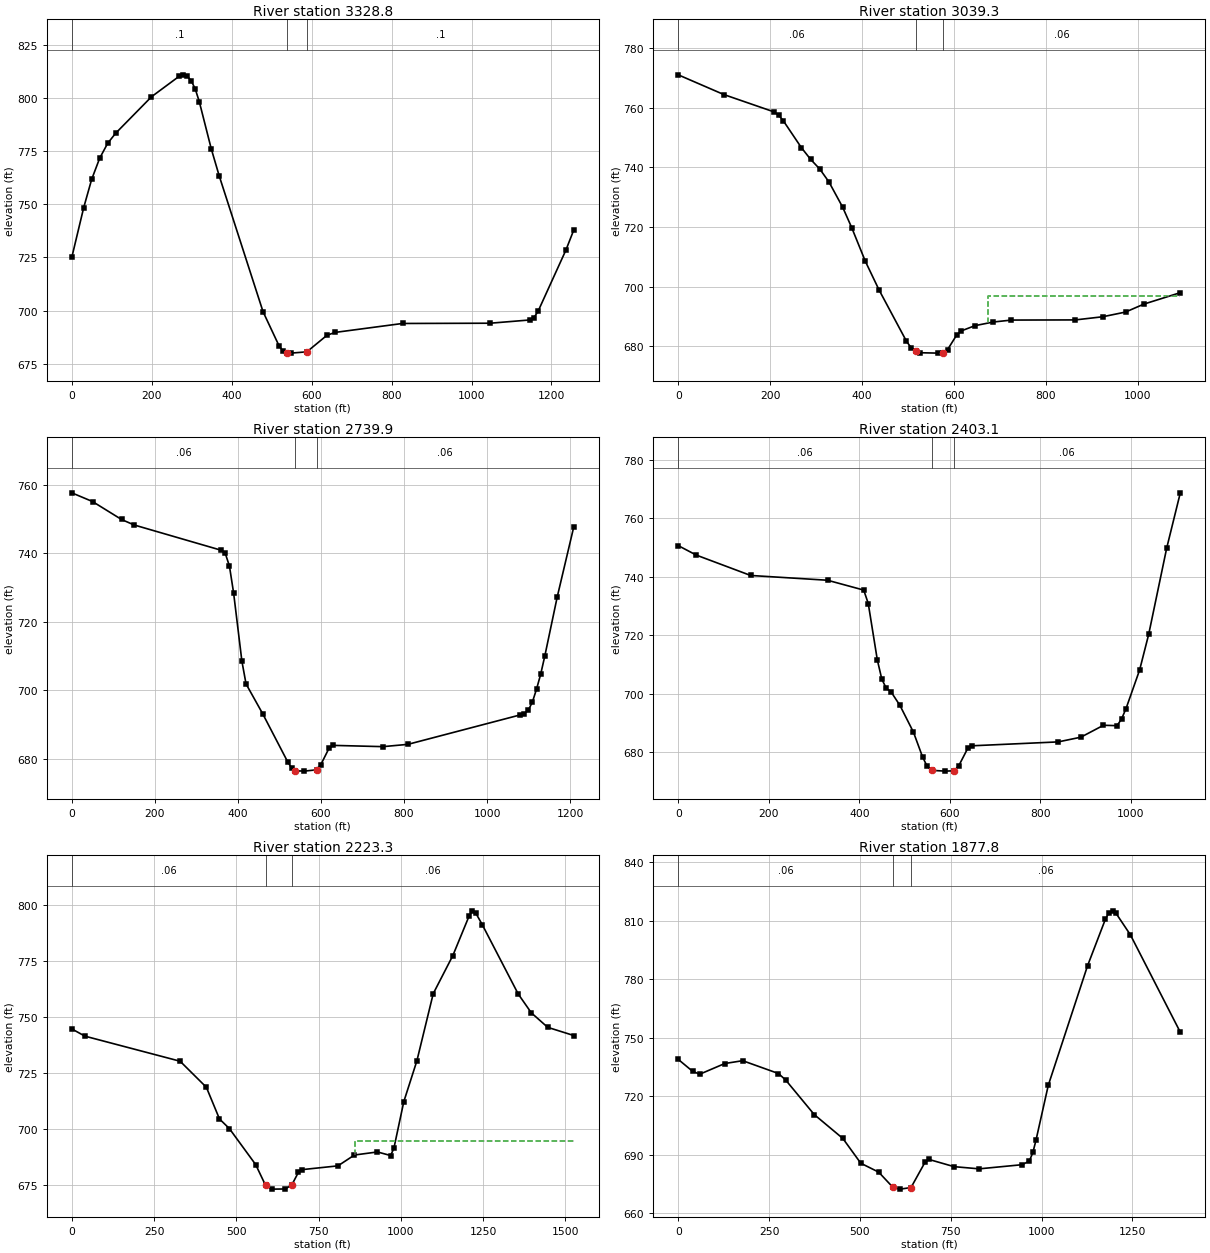
Type RM Length L Ch R = 1 ,3328.8  ,290,289.5,289.1
XS GIS Cut Line= 2
     1913752.892      448878.314     1913465.022       450100.91
#Sta/Elev= 30
       0     725    29.9  748.52    49.8  761.79    69.8  771.72    89.7  778.71
   109.6  783.45   199.4  800.65   269.2  810.37   279.1  810.98   289.1  810.32
     299  808.13     309  804.26     319  798.35   348.9  776.19   368.8  763.43
   478.5  699.47   518.4  683.48   528.3  680.96   538.6  680.09   548.3  679.98
   588.1  680.59     638  688.32   657.9  689.71   827.4  693.94  1046.7  694.06
  1146.4   695.6  1156.3  696.73  1166.3   699.6  1236.1  728.46    1256  738.04
#Mann= 3 , 0 , 0
       0      .1       0   538.6    .045       0   588.1      .1       0
Bank Sta=538.6,588.1
XS Rating Curve= 0 ,0
Exp/Cntr=0.3,0.1

Type RM Length L Ch R = 1 ,3039.3  ,296.6,299.4,302.1
XS GIS Cut Line= 3
     1913455.832      448824.616      1913342.86      449358.807
     1913227.583      449892.498
#Sta/Elev= 30
       0  771.07    99.3  764.44   208.5  758.62   218.4  757.51   228.3   755.7
     268  746.59   287.9   742.7   307.8  739.45   327.6  735.16   357.4   726.7
   377.2  719.81     407  708.45   436.8  698.84   496.4  681.63   506.3   679.5
   516.2  678.24   526.2  677.77   565.9  677.64   575.8  677.75   585.7   678.8
   605.6  683.71   615.5  685.09   645.3  686.86     685  688.08   724.7  688.74
   863.7  688.79   923.2  689.85   972.9  691.43  1012.6  694.09    1092  697.94
#Mann= 3 , 0 , 0
       0     .06       0   516.2    .045       0   575.8     .06       0
#XS Ineff= 2 , 0
                          672.85          696.76
Permanent Ineff=
       F       F
Bank Sta=516.2,575.8
XS Rating Curve= 0 ,0
Exp/Cntr=0.3,0.1

Type RM Length L Ch R = 1 ,2739.9  ,326.4,336.8,347.1
XS GIS Cut Line= 2
     1913231.755      448768.846     1912836.464        449911.5
#Sta/Elev= 30
       0  757.71      50  755.16   119.9  749.91   149.9  748.32   359.7  740.92
   369.7  739.98   379.7  736.29   389.7  728.46   409.7  708.46   419.7  701.81
   459.7  693.11   519.6  679.11   529.6   677.2   538.5  676.42   559.6  676.31
   589.6  676.69   599.6  678.16   619.5     683   629.5  683.84   749.4  683.47
   809.4  684.14  1079.2  692.73  1089.2   693.1  1099.2  694.09  1109.2   696.5
  1119.2  700.27  1129.2  704.64  1139.2     710  1169.1  727.27  1209.1  747.85
#Mann= 3 , 0 , 0
       0     .06       0   538.5    .045       0   589.6     .06       0
Bank Sta=538.5,589.6
XS Rating Curve= 0 ,0
Exp/Cntr=0.3,0.1

Type RM Length L Ch R = 1 ,2403.1  ,179.3,179.8,180.3
XS GIS Cut Line= 3
     1913144.317      448728.097     1912860.315      449037.411
     1912374.866       449527.07
#Sta/Elev= 30
       0  750.66      40  747.41     160  740.44   329.9   738.8   409.9  735.43
   419.9  730.82   439.9  711.52   449.9  704.88   459.9  701.76   469.9  700.66
   489.9  695.93   519.8  686.75   539.8  678.32   549.8  675.14   559.8   673.7
   589.8  673.43   609.8  673.55   619.8  675.25   639.8  681.26   649.8  682.11
   839.6  683.44   889.6  685.05   939.6  689.13   969.5     689   979.5  691.26
   989.5  694.87  1019.5  708.08  1039.5  720.26  1079.4  749.88  1109.4  768.74
#Mann= 3 , 0 , 0
       0     .06       0   559.8    .045       0   609.8     .06       0
Bank Sta=559.8,609.8
XS Rating Curve= 0 ,0
Exp/Cntr=0.3,0.1

Type RM Length L Ch R = 1 ,2223.3  ,327,345.6,364.1
XS GIS Cut Line= 4
     1913082.354      448671.359     1912661.085      448991.111
      1912312.51      449321.519     1911814.588      449182.859
#Sta/Elev= 30
       0  744.68    39.9  741.44   329.3  730.24   409.1  718.61     449  704.45
     479  700.17   558.9   684.1   588.9  674.85   608.9  673.13     649   673.2
     669  675.08     689  680.67     699  681.82     809  683.52   859.1  688.36
   929.1  689.73   969.1  688.13   979.1  691.42  1009.2  712.21  1048.9   730.4
  1098.6  760.42  1158.3  777.45    1208   795.2  1217.9   797.4  1227.8  796.43
  1247.7  791.21    1357  760.24  1396.8  751.85  1446.5  745.38    1526  741.71
#Mann= 3 , 0 , 0
       0     .06       0   588.9    .045       0     669     .06       0
#XS Ineff= 2 , 0
                          860.15          694.66
Permanent Ineff=
       F       F
Bank Sta=588.9,669
XS Rating Curve= 0 ,0
Exp/Cntr=0.3,0.1

Type RM Length L Ch R = 1 ,1877.8  ,323.7,326.7,329.7
XS GIS Cut Line= 5
     1913051.128      448608.083     1912595.142      448766.626
     1912102.598      448737.092     1912061.023      448728.956
     1911790.269      448971.469
#Sta/Elev= 30
       0  738.86    39.4  732.77    59.1  731.25   128.1  736.74   177.3  738.19
   275.9  731.61   295.6  728.31   374.4  710.56   453.2   698.3   502.5  685.61
   551.8  681.04   591.3  673.17     611  672.33   640.7  673.13   680.1  686.38
     690  687.56   759.1  683.86   828.2  682.73   946.6  684.86   966.3   686.7
   976.2  691.13   984.7  697.39  1018.6  725.59  1126.6  786.84  1175.7  810.69
  1185.6  814.11  1195.4  815.04  1205.2  813.71  1244.5  802.76    1382  752.79
#Mann= 3 , 0 , 0
       0     .06       0   591.3    .045       0   640.7     .06       0
#XS Ineff= 2 , 0
                             690          687.56
Permanent Ineff=
       F       F
Bank Sta=591.3,640.7
XS Rating Curve= 0 ,0
Exp/Cntr=0.3,0.1

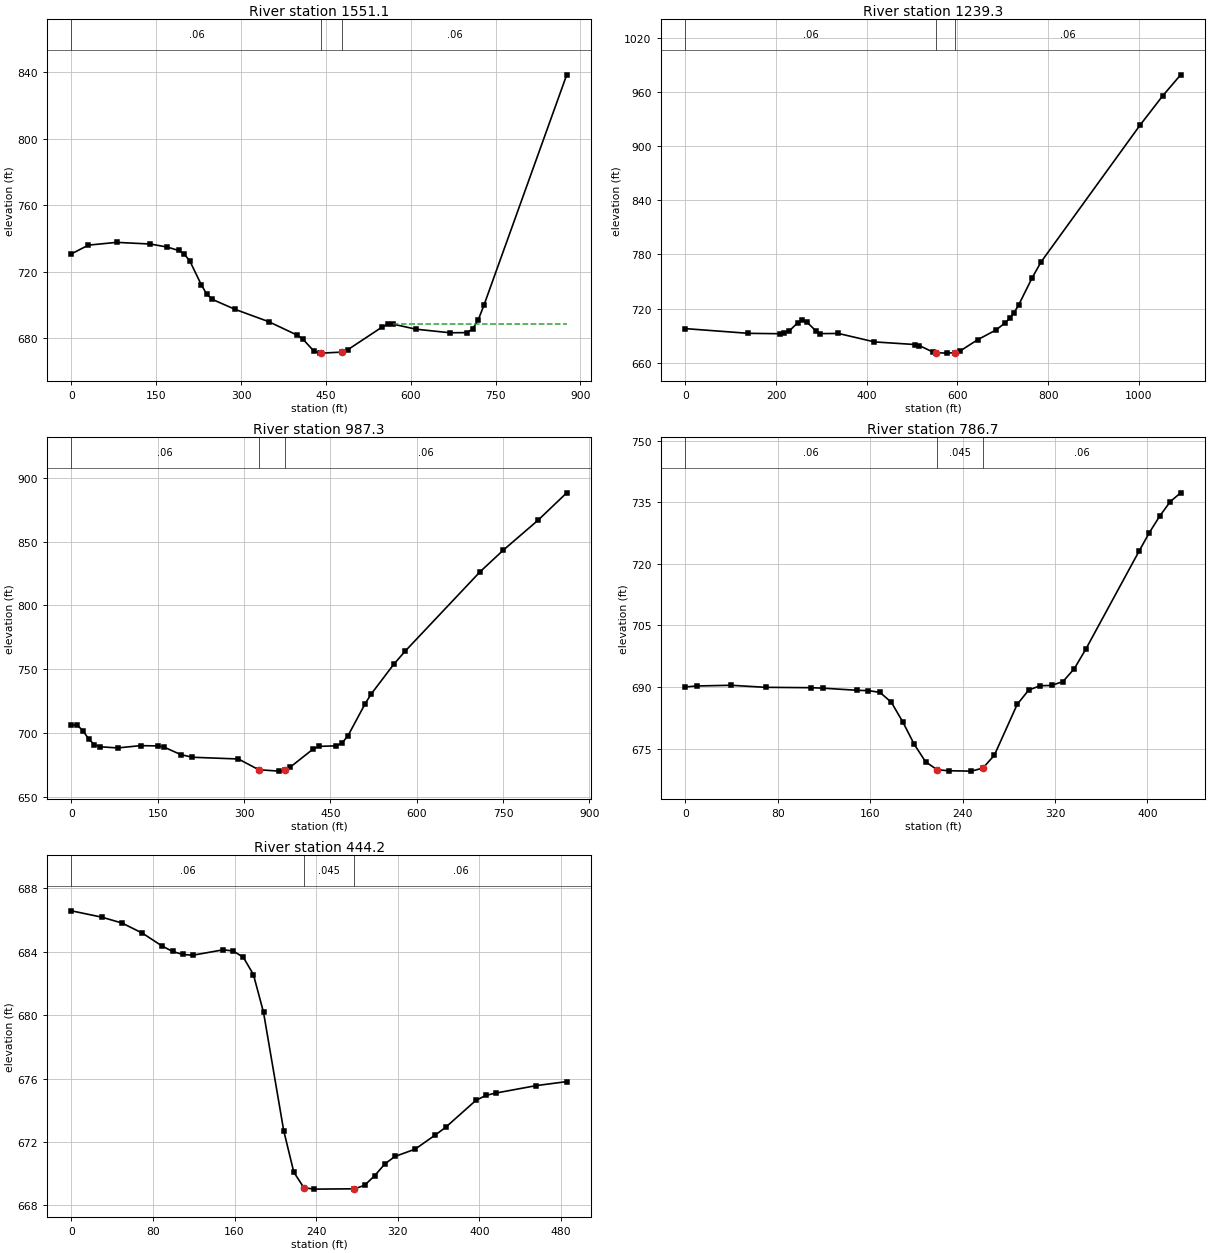
Type RM Length L Ch R = 1 ,1551.1  ,306.5,311.8,317.1
XS GIS Cut Line= 4
     1912955.721      448554.768     1912620.405      448457.915
     1912257.011      448386.404     1912111.096      448330.283
#Sta/Elev= 30
       0  730.82    29.9  736.07    79.8  737.74   139.6  736.74   169.5  734.91
   189.5  732.86   199.4  730.75   209.4  726.49   229.4  712.38   239.3  706.51
   249.3  703.42   289.2  697.47     349  690.01   399.1  681.96   409.1   679.6
   429.1  672.17   439.1  671.13   441.9  671.13   479.2  671.76   489.2   673.3
   549.2   686.8   559.2  688.38   569.2  688.51   609.3  685.51   669.3  683.38
   699.4  683.46   709.4  685.68   719.4  691.28   729.2  699.83   875.7  838.49
#Mann= 3 , 0 , 0
       0     .06       0   441.9    .045       0   479.2     .06       0
#XS Ineff= 2 , 0
                          569.21          688.52
Permanent Ineff=
       F       F
Bank Sta=441.9,479.2
XS Rating Curve= 0 ,0
Exp/Cntr=0.3,0.1

Type RM Length L Ch R = 1 ,1239.3  ,249.3,252,254.7
XS GIS Cut Line= 3
     1913113.936      448370.431     1912617.587      448142.936
     1912121.238      447915.442
#Sta/Elev= 30
       0  697.69     139  692.46   208.5  692.03   218.4  692.72   228.3  694.78
   248.2  704.41   258.1   706.8     268  704.96   287.9  695.09   297.8  692.15
   337.5  692.31     417  682.95   506.3  680.04   516.2  678.82     546  671.66
   553.5  670.99   575.8  670.51   595.6  671.05   605.6  672.85   645.3  685.61
     685   696.2   704.8  703.96   714.8  708.97   724.7  715.42   734.6  723.64
   764.4  753.85   784.2  771.59  1002.6  923.42  1052.3  955.78    1092  979.14
#Mann= 3 , 0 , 0
       0     .06       0   553.5    .045       0   595.6     .06       0
Bank Sta=553.5,595.6
XS Rating Curve= 0 ,0
Exp/Cntr=0.3,0.1

Type RM Length L Ch R = 1 ,987.3   ,194,200.6,207.1
XS GIS Cut Line= 2
     1913023.067      448095.977     1912288.831       447647.05
#Sta/Elev= 30
       0  706.08      10   706.2      20  701.76      30  695.25      40  690.84
      50  689.21    80.1  688.29   120.1  690.09   150.1  689.87   160.1   689.1
   190.1  683.05   210.2  680.99   290.2  679.63   325.4  671.22   360.2  670.12
   370.3  670.68   380.3   673.3   420.3  687.55   430.3  689.51   460.3  689.95
   470.3  692.23   480.3  697.67   510.4  722.96   520.4  730.27   560.4  754.03
   580.4  764.37   710.5  826.53   750.5  843.31   810.6  866.65   860.6  888.18
#Mann= 3 , 0 , 0
       0     .06       0   325.4    .045       0   370.3     .06       0
Bank Sta=325.4,370.3
XS Rating Curve= 0 ,0
Exp/Cntr=0.3,0.1

Type RM Length L Ch R = 1 ,786.7   ,332,342.4,352.8
XS GIS Cut Line= 3
     1913002.022      447927.613     1912763.506      447662.439
     1912720.012      447604.915
#Sta/Elev= 30
       0  690.03     9.9  690.27    39.6  690.44    69.4  689.94     109  689.85
   118.9  689.74   148.6  689.22   158.5  689.13   168.4  688.73   178.3  686.31
   188.2  681.54   198.1   676.1     208   671.8     218  669.88   227.9  669.63
   247.7  669.54   257.6  670.28   267.5  673.41   287.3  685.79   297.2  689.26
   307.1  690.33     317   690.4   326.9  691.34   336.8  694.51   346.8  699.29
   392.7  723.04   401.7   727.6   410.8  731.67   419.8  735.14   428.8  737.29
#Mann= 3 , 0 , 0
       0     .06       0     218    .045       0   257.6     .06       0
Bank Sta=218,257.6
XS Rating Curve= 0 ,0
Exp/Cntr=0.3,0.1

Type RM Length L Ch R = 1 ,444.2   ,444.3,444.2,444.1
XS GIS Cut Line= 2
     1913177.401      447780.294     1913044.113      447313.084
#Sta/Elev= 30
       0  686.58    29.8  686.18    49.6  685.81    69.4  685.18    89.2  684.35
    99.2  684.02   109.1  683.83     119  683.78   148.7  684.12   158.6  684.05
   168.6  683.65   178.5  682.56   188.4  680.18   208.2  672.72   218.1   670.1
     228  669.12     238  669.03   277.6  669.05   287.5  669.27   297.5  669.88
   307.4  670.62   317.3  671.09   337.1  671.55     357  672.45   366.9  672.92
   396.6  674.62   406.5  674.94   416.4  675.09   456.1  675.56   485.8  675.81
#Mann= 3 , 0 , 0
       0     .06       0     228    .045       0   277.6     .06       0
Bank Sta=228,277.6
XS Rating Curve= 0 ,0
Exp/Cntr=0.3,0.1

Chan Stop Cuts=-1
Use User Specified Reach Order=0
Composite Channel Slope=5